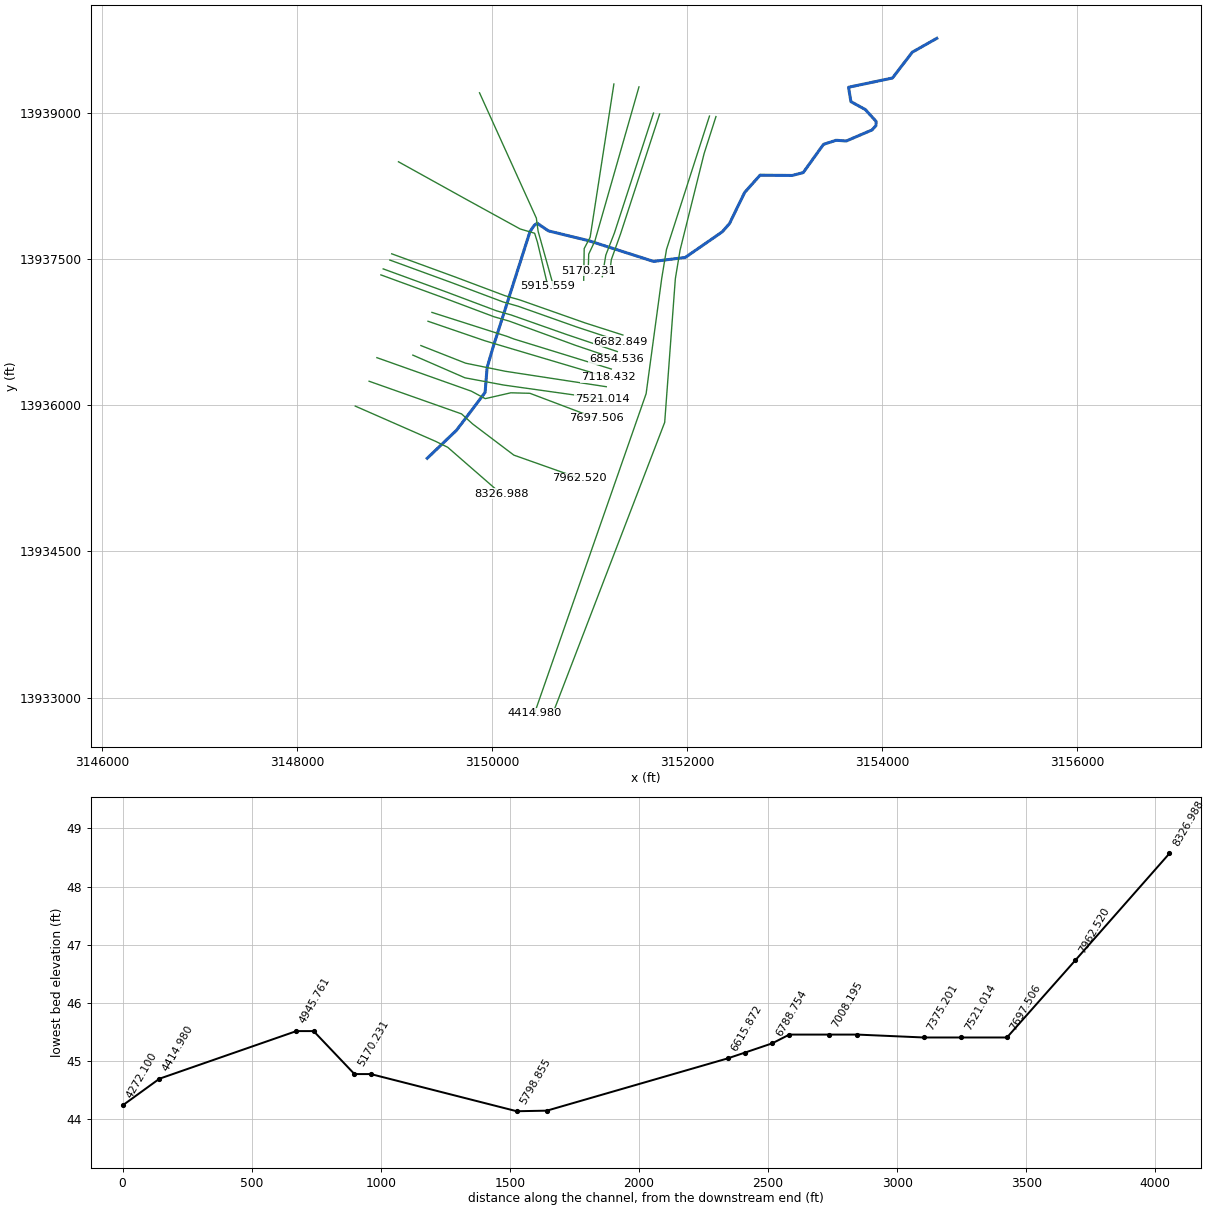
--- G103-48-00.prj (project) ---

Proj Title=G103-48-00
Current Plan=p02
Default Exp/Contr=.3,.1
English Units
Geom File=g07
Flow File=f01
Flow File=f02
Plan File=p01
Plan File=p02
Y Axis Title=Elevation
X Axis Title(PF)=Main Channel Distance
X Axis Title(XS)=Station
BEGIN DESCRIPTION:
San Jacinto River Watershed
Blacks Branch
HCFCD Unit G103-48-00
Flood Hazard Model
10, 2, 1, 0.2% Event
Filename G1034800.prj
Prepared by:  FTN Associates   DATE: May 2003
Reviewed by:                            DATE:
Status: (FINAL RAS)
LIDAR3 Data, with survey data in geometry and structures included.
Downstream slope is 0.002273 ft/ft, calculated from RS 1074.588 and RS 568.69
FLow Paths have been edited.  ajp 10/28/02
END DESCRIPTION:
DSS Export Rating Curves= 0
DSS Export Rating Curve Sorted= 0
DSS Export Volume Flow Curves= 0
DXF OffsetX= 0
DXF OffsetY= 0
DXF ScaleX= 1
DXF ScaleY= 10

--- G103-48-00.p02 (plan) ---

Plan Title=Floodway
Version=Version 3.0.1  Mar 2001
Short Identifier=Floodway0607
Geom File=g07
Flow File=f02
Subcritical Flow
K Sum by GR= 0
Std Step Tol= 0.01
Critical Tol= 0.01
Num of Std Step Trials= 20
Max Error Tol= 0.3
Flow Tol Ratio= 0.001
Split Flow NTrial= 30
Split Flow Tol= 0.02
Split Flow Ratio= 0.02
Log Output Level= 0
Friction Slope Method= 1
Unsteady Friction Slope Method= 2
Parabolic Critical Depth
Global Vel Dist= 0 , 0 , 0
Global Log Level= 0
CheckData=True
Encroach Param=-1 ,0,0, 2
Encroach River=G103-48-00
Encroach Reach=Blacks Branch
Encroach Node=8326.988
       1  939.15 1017.12
Encroach Node=7962.520
       1    1002    1110
Encroach Node=7697.506
       1 1085.55 1193.16
Encroach Node=7521.014
       1   712.8  825.56
Encroach Node=7448
       1     714     829
Encroach Node=7375.201
       1  709.89  829.55
Encroach Node=7118.432
       1  652.68  767.62
Encroach Node=7063
       1  652.95  766.94
Encroach Node=7008.195
       1  652.68  767.62
Encroach Node=6854.536
       1 1274.99 1445.39
Encroach Node=6788.754
       1    1260    1420
Encroach Node=6735.802
       1 1244.02    1405
Encroach Node=6682.849
       1 1244.02    1405
Encroach Node=6615.872
       1 1246.81 1396.89
Encroach Node=5915.559
       1 1474.28  1546.7
Encroach Node=5798.855
       1 1452.79 1521.01
Encroach Node=5233.642
       1 1604.57 1672.77
Encroach Node=5170.231
       1 1638.93 1709.54
Encroach Node=5089.696
       1 1638.93 1709.54
Encroach Node=5012.007
       1 1638.93 1709.54
Encroach Node=4945.761
       1 1638.93 1709.54
Encroach Node=4680.37
       1 1638.93 1716.88
Encroach Node=4414.980
       1 1638.93 1716.88
Encroach Node=4272.100
       1 1483.44    1600
Encroach Node=3586.981
       1 1120.99 1250.46
Encroach Node=3120.168
       1  808.71    1000
Encroach Node=2787.609
       1  961.72 1237.46
Encroach Node=2738.42
       1  966.68 1205.92
Encroach Node=2689.225
       1     961 1205.33
Encroach Node=2287.037
       1     400     950
Encroach Node=1074.588
       1     125     400
Encroach Node=568.690
       1  174.45  369.45
Encroach Reach=G103-48-00_0006
Encroach Node=8326.988
       1  939.15 1017.12
Encroach Node=7962.520
       1    1002    1110
Encroach Node=7697.506
       1 1085.55 1193.16
Encroach Node=7521.014
       1   712.8  825.56
Encroach Node=7448
       1     714     829
Encroach Node=7375.201
       1  709.89  829.55
Encroach Node=7118.432
       1  652.68  767.62
Encroach Node=7063
       1  652.95  766.94
Encroach Node=7008.195
       1  652.68  767.62
Encroach Node=6854.536
       1 1274.99 1445.39
Encroach Node=6788.754
       1    1260    1420
Encroach Node=6735.802
       1 1244.02    1405
Encroach Node=6682.849
       1 1244.02    1405
Encroach Node=6615.872
       1 1246.81 1396.89
Encroach Node=5915.559
       1 1474.28  1546.7
Encroach Node=5798.855
       1 1452.79 1521.01
Encroach Node=5233.642
       1 1604.57 1672.77
Encroach Node=5170.231
       1 1638.93 1709.54
Encroach Node=5089.696
       1 1638.93 1709.54
Encroach Node=5012.007
       1 1638.93 1709.54
Encroach Node=4945.761
       1 1638.93 1709.54
Encroach Node=4680.37
       1 1638.93 1716.88
Encroach Node=4414.980
       1 1638.93 1716.88
Encroach Node=4272.100
       1 1483.44    1600
Encroach Node=3586.981
       1 1120.99 1250.46
Encroach Node=3120.168
       1  808.71    1000
Encroach Node=2787.609
       1  961.72 1237.46
Encroach Node=2738.42
       1  966.68 1205.92
Encroach Node=2689.225
       1     961 1205.33
Encroach Node=2287.037
       1     400     950
Encroach Node=1074.588
       1     125     400
Encroach Node=568.690
       1  174.45  369.45
Computation Interval=1HOUR
Output Interval=1HOUR
Run HTab= 0
Run UNet= 0
Run PostProcess= 0
UNET Theta= 1
UNET ZTol= 0.02
UNET ZSATol= 0.1
UNET MxIter= 20
UNET MaxInSteps= 20
UNET DtIC= 0
UNET DtMin= 0
UNET MaxCRTS= 20
UNET WFStab= 2
UNET SFStab= 1
UNET WFX= 1
UNET SFX= 1
UNET Convert EG Bridges=-1
UNET Use Existing IB Tables=-1
Instantaneous Interval=1HOUR
Write IC File= 0
IC Time=0
Write Velocity= 0
Write Detailed= 0

--- G103-48-00.p01 (plan) ---

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Plan Title=FEMA Effective June 2007
Short Identifier=FEMAeff0607
Geom File=g07
Flow File=f01
Encroach Param=-1 ,0,0, 0

--- G103-48-00.f02 (steady flow) ---

Flow Title=Floodway
Version=Version 3.0.1  Mar 2001
Number of Profiles= 2
Profile Names=1PCT_100yr, 1PCTFloodway_100yrFW
River Rch & RM=G103-48-00,G103-48-00_0006    ,8326.988
    1259    1259
River Rch & RM=G103-48-00,G103-48-00_0006    ,7962.520
    1279    1279
River Rch & RM=G103-48-00,G103-48-00_0006    ,7697.506
    2081    2081
River Rch & RM=G103-48-00,G103-48-00_0006    ,7521.014
    2142    2142
River Rch & RM=G103-48-00,G103-48-00_0006    ,7375.201
    2255    2255
River Rch & RM=G103-48-00,G103-48-00_0006    ,7118.432
    2306    2306
River Rch & RM=G103-48-00,G103-48-00_0006    ,7008.195
    2410    2410
River Rch & RM=G103-48-00,G103-48-00_0006    ,6788.754
    2531    2531
River Rch & RM=G103-48-00,G103-48-00_0006    ,5798.855
    2604    2604
River Rch & RM=G103-48-00,G103-48-00_0006    ,5233.642
    2731    2731
River Rch & RM=G103-48-00,G103-48-00_0006    ,4272.100
    3061    3061
Boundary for River Rch & Prof#=G103-48-00,G103-48-00_0006    , 1
Up Type= 0
Dn Type= 3
Dn Slope=2.273185E-03
DSS Import GetInterval= 0
DSS Import GetPeak= 0
DSS Import FillOption= 0

--- G103-48-00.f01 (steady flow) ---

Flow Title=FEMA Effective June 2007
Version=Version 3.0.1  Mar 2001
Number of Profiles= 4
Profile Names=10PCT_10yr, 2PCT_50yr, 1PCT_100yr, 0.2PCT_500yr
River Rch & RM=G103-48-00,G103-48-00_0006    ,8326.988
     807    1105    1259    1661
River Rch & RM=G103-48-00,G103-48-00_0006    ,7962.520
     820    1124    1279    1689
River Rch & RM=G103-48-00,G103-48-00_0006    ,7697.506
    1273    1802    2081    2843
River Rch & RM=G103-48-00,G103-48-00_0006    ,7521.014
    1312    1852    2142    2942
River Rch & RM=G103-48-00,G103-48-00_0006    ,7375.201
    1385    1945    2255    3123
River Rch & RM=G103-48-00,G103-48-00_0006    ,7118.432
    1418    1985    2306    3205
River Rch & RM=G103-48-00,G103-48-00_0006    ,7008.195
    1484    2070    2410    3373
River Rch & RM=G103-48-00,G103-48-00_0006    ,6788.754
    1562    2183    2531    3540
River Rch & RM=G103-48-00,G103-48-00_0006    ,5798.855
    1608    2251    2604    3638
River Rch & RM=G103-48-00,G103-48-00_0006    ,5233.642
    1689    2371    2731    3813
River Rch & RM=G103-48-00,G103-48-00_0006    ,4272.100
    1891    2659    3061    4301
Boundary for River Rch & Prof#=G103-48-00,G103-48-00_0006    , 1
Up Type= 0
Dn Type= 3
Dn Slope=2.273185E-03
DSS Import GetInterval= 0
DSS Import GetPeak= 0
DSS Import FillOption= 0

--- G103-48-00.g07 (geometry) ---

Geom Title=G103-48-00 June 2007
Version=Version 3.0.1  Mar 2001

River Reach=G103-48-00      ,G103-48-00_0006
Reach XY= 30
     3149335.387    13935453.976     3149636.434    13935741.961
     3149929.015    13936128.776     3149949.612    13936383.796
     3150008.711     13936587.25     3150389.751    13937779.705
     3150434.149    13937844.285     3150463.412    13937864.466
     3150578.584     13937786.29     3150996.091    13937684.263
     3151656.993    13937472.932     3151982.507    13937513.853
     3152361.437    13937776.606     3152435.666    13937860.649
     3152591.182    13938180.405      3152749.49    13938357.569
       3153078.5    13938354.656     3153192.249    13938384.293
     3153400.051    13938673.796     3153529.332    13938715.622
     3153633.685    13938708.396     3153897.739    13938821.416
       3153938.4    13938866.479     3153939.284    13938909.775
     3153828.792    13939030.826     3153681.174    13939112.116
     3153656.754    13939259.469      3154107.54    13939354.274
     3154311.195    13939619.514     3154562.082    13939761.186

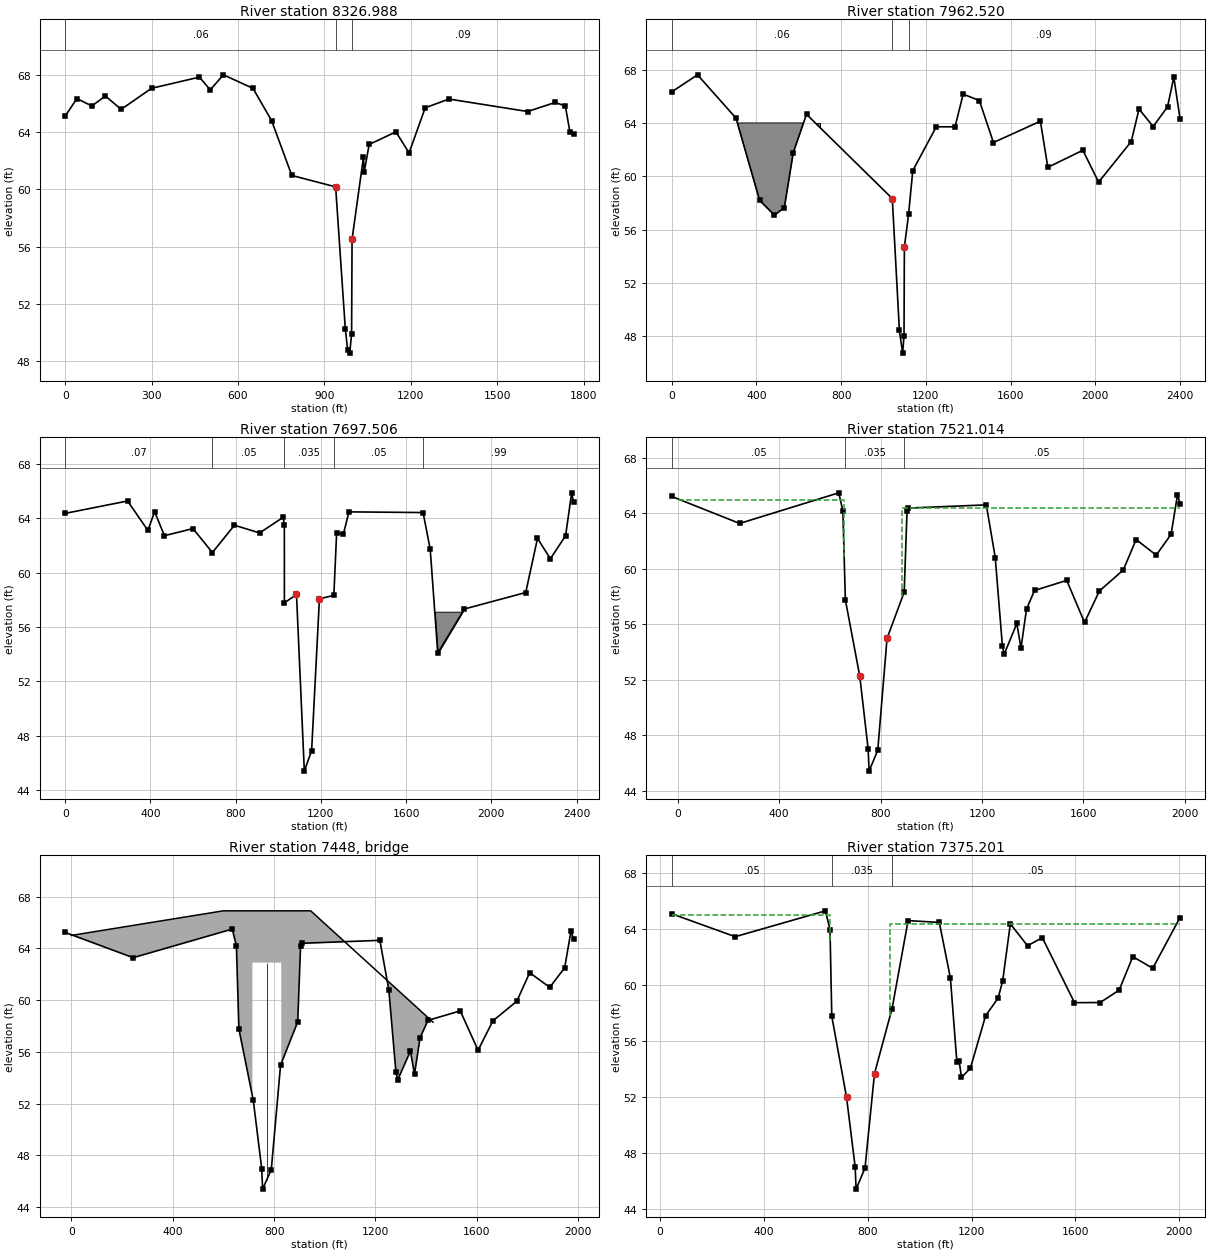
Type RM Length L Ch R = 1 ,8326.988,378.84,364.47,356.87
BEGIN DESCRIPTION:
422v1
Bank Station offset =      4012
END DESCRIPTION:
XS GIS Cut Line= 6
     3148597.206    13935988.976     3149423.645    13935626.454
     3149430.839    13935622.902     3149534.156    13935572.166
     3149545.367    13935566.645     3150093.775    13935089.012
#Sta/Elev= 30
       0   65.11    40.5   66.33   92.44   65.82  139.77   66.51  194.25   65.58
  299.95   67.05  466.15   67.83  503.63   66.94  549.36   67.99  651.91   67.05
  716.94   64.79  786.89   60.97  939.15   60.17  972.68   50.28   980.9   48.78
  988.01   48.57  994.57   49.89  996.19   56.52 1035.88   62.26 1038.08   61.18
 1055.53   63.13 1148.53   64.01 1194.19   62.54 1250.21   65.69 1332.58    66.3
 1605.82   65.43 1701.51   66.06 1736.77   65.82 1752.98   63.99 1765.32   63.85
#Mann= 3 , 0 , 0
       0     .06       0  939.15     .03       0  996.19     .09       0
Bank Sta=939.15,996.19
XS Rating Curve= 0
Exp/Cntr=.3,.1

Type RM Length L Ch R = 1 ,7962.520,250.91,265.01,290.59
BEGIN DESCRIPTION:
Copy of 422v1.  Adjusted elevations down 1.84 ft between banks proportional to slope between surveyed sections.
Low LOB at power line easement, low ROB areas are not connected to channel.
Bank Station offset =      3910
Manning's n values applied are obtained from existing FIS HEC-2 study.
END DESCRIPTION:
XS GIS Cut Line= 5
     3148739.341    13936243.963     3149687.764    13935908.922
     3149801.162    13935805.832     3150223.829    13935486.255
      3150893.91    13935249.149
#Sta/Elev= 30
       0   66.33     122   67.61  303.71   64.36   415.2   58.19  485.08   57.08
  531.95   57.65  573.91   61.76  636.54   64.65 1041.51   58.33 1075.04   48.44
 1090.37   46.73 1096.93   48.05 1098.55   54.68 1118.39   57.14 1138.24   60.42
 1249.13   63.71  1337.7   63.71 1376.07   66.16 1452.65   65.68 1519.06   62.53
 1740.69   64.13 1775.87   60.67 1941.22   61.95 2015.48   59.56 2169.36    62.6
 2206.39   65.04 2273.14   63.73 2340.96   65.21 2370.61   67.43 2399.79   64.33
#Mann= 3 ,-1 , 0
       0     .06       0 1041.51    .033       0 1118.39     .09       0
#Block Obstruct= 2 , 0
       0     700      64    1400       0      66
Bank Sta=1041.51,1098.55
XS Rating Curve= 0
Exp/Cntr=.3,.1

Type RM Length L Ch R = 1 ,7697.506,148.56,176.49,172.84
BEGIN DESCRIPTION:
422v2.  XS 4/4 for 422s10, South Target Center Bridge.  LIDAR Overbanks with interpolated and reconnaissance elevations between banks.  Flow in far ROB not effective, does not re-enter channel.
Bank Station offset =      3879
END DESCRIPTION:
XS GIS Cut Line= 6
     3148819.341    13936485.787     3149788.228    13936141.921
     3149930.604    13936065.478     3150192.902     13936125.41
     3150388.772    13936120.255      3151068.98    13935863.118
#Sta/Elev= 30
       0   64.35  292.65   65.26  388.06    63.1  419.61   64.47  465.76   62.71
  599.67   63.23  690.92   61.47  794.42   63.48  912.33   62.91 1023.19   64.06
 1028.56    63.5 1028.75   57.77 1085.55   58.39 1122.33    45.4 1156.58   46.91
 1193.16   58.07 1260.84   58.32 1273.97   62.92 1305.27   62.81 1331.83   64.46
 1679.72   64.41 1713.19   61.71 1748.64   54.07 1873.46   57.32 2161.44   58.53
 2216.69   62.51 2277.28   61.01 2348.57   62.71 2377.05   65.86 2385.82   65.18
#Mann= 5 ,-1 , 0
       0     .07       0  690.92     .05       0 1028.75    .035       0
 1260.84     .05       0 1679.72     .99       0
#Block Obstruct= 1 ,-1
 1444.64 2201.07   57.12
Bank Sta=1085.55,1193.16
XS Rating Curve= 0
Exp/Cntr=.5,.3

Type RM Length L Ch R = 1 ,7521.014,146.32,145.81,144.3
BEGIN DESCRIPTION:
XS 3/4 for 422s10, South Target Center Bridge.  LIDAR Overbanks with interpolated and reconnaissance elevations between banks.  Interpolation performed between nearest surveyed sections (7702 and 6854). LIDAR values used betweeen banks where banks wider than copied survey data.  (more below)
 Flow ineffective in low area beyond ROB, does not re-enter channel. Normal ineffective elevations set at high banks.
Bank Station offset =      4221
END DESCRIPTION:
XS GIS Cut Line= 4
      3149187.78    13936511.995     3149722.612    13936279.197
     3150121.222     13936204.66     3151127.794    13936063.364
#Sta/Elev= 30
     -24   65.23  244.12   63.28  635.12   65.49   651.4   64.18  661.15   57.77
  717.95   52.26  751.11   46.99  754.73    45.4  788.98   46.91  825.56   54.98
  893.24   58.32  904.42   64.17  908.51   64.39 1217.24   64.62 1252.48   60.81
 1280.65   54.43 1287.72   53.84 1337.67   56.06 1353.96   54.28 1375.83    57.1
 1407.37   58.44 1534.41   59.17 1604.65   56.13 1663.13    58.4 1757.59   59.92
 1808.21   62.12  1887.5   60.99 1946.24    62.5 1971.33   65.35 1981.26   64.71
#Mann= 3 ,-1 , 0
     -24     .05       0  661.15    .035       0  893.24     .05       0
#XS Ineff= 2 , 0
       0  656.44      65  886.43       0   64.39
Permanent Ineff=
       F       F
Bank Sta=717.95,825.56
XS Rating Curve= 0
Exp/Cntr=.5,.3

Type RM Length L Ch R = 3 ,7448    ,,,
BEGIN DESCRIPTION:
422s10, "ACCESS ROAD"
S. Target Bridge.
This data comprised of elevation and distance estimates using hand level, pacing, and ocular estimation from digital photos, supported by TIN elevation and aerial photography.  Data obtained by FTN on Jan. 20, 2003.
END DESCRIPTION:
Bridge Culvert--1,0,-1,-1, 0
Deck Dist Width WeirC Skew NumUp NumDn MinLoCord MaxHiCord MaxSubmerge Is_Ogee
59.91,30,2.6,0, 8, 8, , , .95, 0, 0,0,,
       0  599.43  714.43  714.44  828.43  828.44  944.43    1427
      65    66.9    66.9    66.9    66.9    66.9    66.9    58.3
                            62.9    62.9
       0  599.43  714.43  714.44  828.43  828.44  944.43    1280
      65    66.9    66.9    66.9    66.9    66.9    66.9    58.3
                            62.9    62.9
Pier Skew, UpSta & Num, DnSta & Num=  ,771, 2 ,771, 2 , 0 , 0 , 0 ,,
     1.5     1.5
      40    62.9
     1.5     1.5
      40    62.9
BR Coef=-1 , 0 , 0 ,, 0 ,,,.8,-1,,1,
WSPro=,,,, 1 ,,,, 0 ,,,, 0 ,,,,-1 ,-1 ,-1 , 0 , 0 , 0 , 0 , 0
BC Design=,, 0 ,, 0 ,,,,,,

Type RM Length L Ch R = 1 ,7375.201,262.69,256.77,251.14
BEGIN DESCRIPTION:
XS 2/4 for 422s10, South Target Center Bridge. XS 4/4 for 422s09, North Target Center Bridge.  LIDAR Overbanks with interpolated and reconnaissance elevations between banks.  Interpolation performed between nearest surveyed sections (7702 and 6854). LIDAR values used betweeen banks where banks wider than copied survey data. (more below)
  Flow ineffective in low area beyond ROB, does not re-enter channel. Normal ineffective elevations set at high banks.
Bank Station offset =      4290
END DESCRIPTION:
XS GIS Cut Line= 4
     3149270.251     13936609.93     3149730.389    13936428.919
     3150137.444    13936346.046     3151171.868    13936187.808
#Sta/Elev= 30
      46    65.1  290.48   63.46  637.79   65.31  655.35   63.97  662.18   57.77
  718.98   51.97  752.14   46.99  755.76    45.4  790.01   46.91  826.59   53.67
  894.27   58.32  955.87   64.61 1076.04   64.48 1118.72    60.5 1143.54    54.5
  1152.2   54.59 1161.36   53.39 1195.65   54.05 1254.42   57.82 1302.21   59.06
 1319.93   60.31 1349.35   64.38 1415.43   62.81  1472.4   63.39 1596.29   58.74
 1695.05   58.75 1767.94   59.63 1820.77   62.03  1897.5    61.2 2002.32   64.83
#Mann= 3 ,-1 , 0
      46     .05       0  662.18    .035       0  894.27     .05       0
#XS Ineff= 2 , 0
       0  656.44      65  886.43       0   64.39
Permanent Ineff=
       F       F
Bank Sta=718.98,826.59
XS Rating Curve= 0
Exp/Cntr=.5,.3

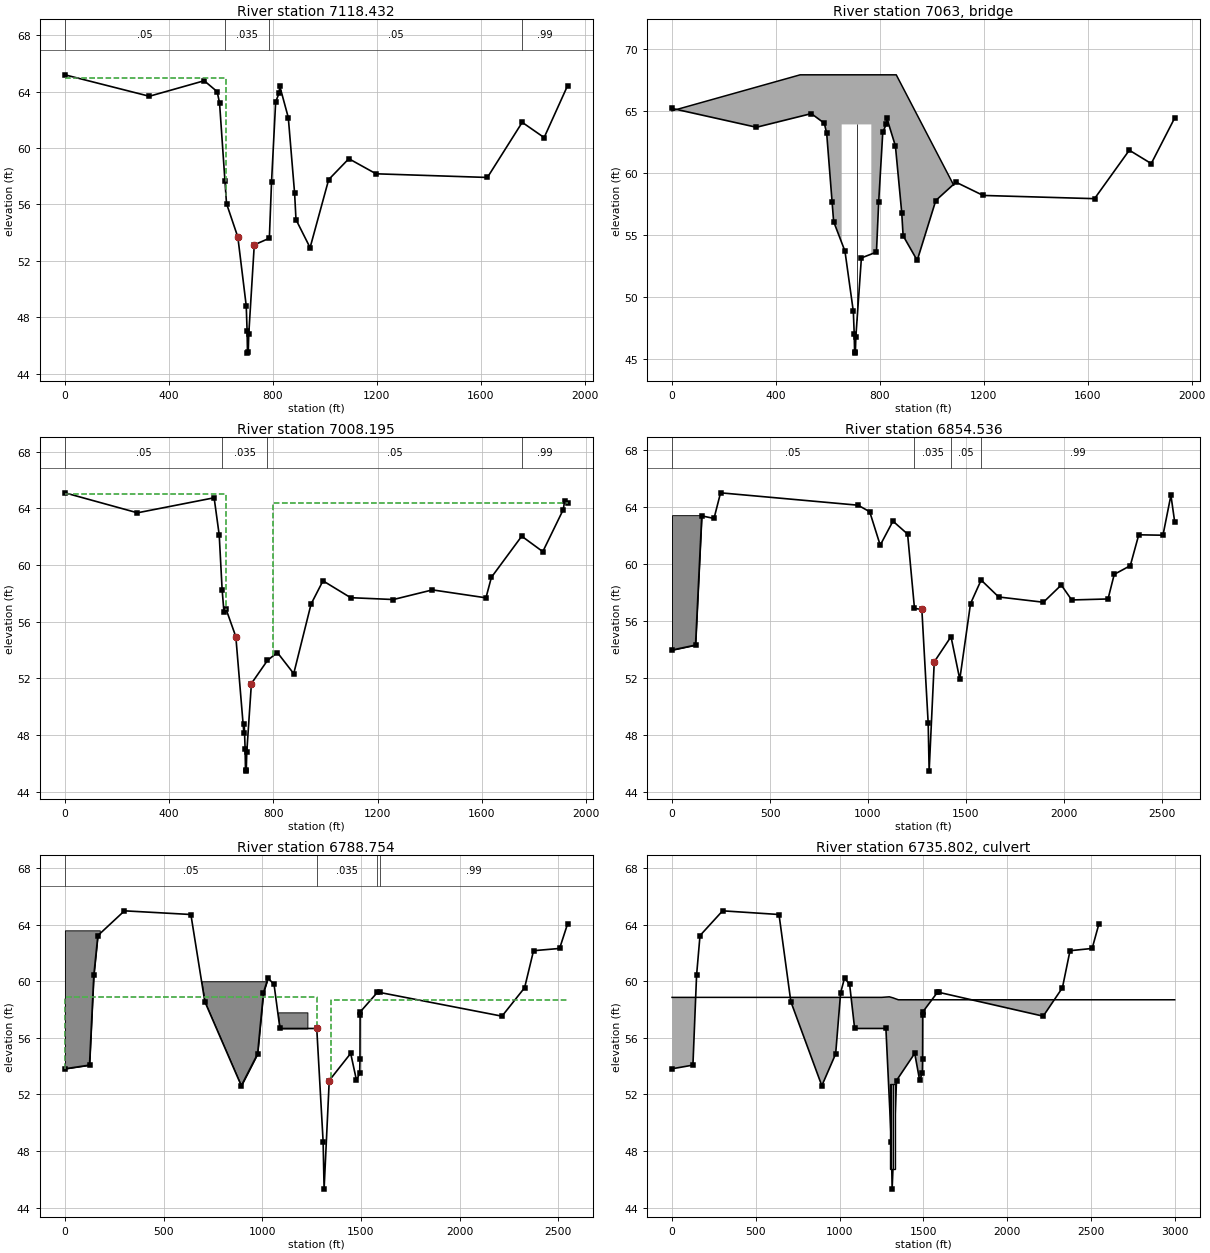
Type RM Length L Ch R = 1 ,7118.432,111.52,110.24,109.42
BEGIN DESCRIPTION:
XS 1/4 for 422s10, Access Road (South Target Center Bridge).  XS 3/4 for 422s09, North Target Center Bridge.  LIDAR Overbanks with interpolated and reconnaissance elevations between banks.  Interpolation performed between nearest surveyed sections (7702 and 6854). LIDAR values used betweeen banks where banks wider than copied survey data. (more below)
 Flow ineffective in low area beyond ROB, does not re-enter channel. Normal ineffective elevations set at high banks.
Bank Station offset =      4297
END DESCRIPTION:
XS GIS Cut Line= 4
     3149343.446    13936859.289     3149925.974    13936659.392
      3150105.37    13936605.681     3151190.016    13936283.734
#Sta/Elev= 30
       0   65.19  324.81   63.67  536.05   64.77  585.78      64  595.07    63.2
  615.87   57.67   621.9   56.06  665.49   53.68  697.76   48.81  701.09   47.03
  702.66   45.45  705.62   45.56  707.47   46.78  728.76   53.13  786.75    53.6
  795.26   57.62  811.06   63.27  824.32    63.9   826.7    64.4  859.67   62.16
  884.01   56.78  889.29   54.92  943.55   52.93  1015.1   57.76  1092.7   59.24
 1197.38   58.17 1625.99   57.91 1759.89   61.82 1844.31   60.74 1934.55   64.42
#Mann= 4 ,-1 , 0
       0     .05       0  615.87    .035       0  786.75     .05       0
 1759.89     .99       0
#XS Ineff= 2 , 0
       0     620      65   826.7       0    64.4
Permanent Ineff=
       F       F
Bank Sta=665.49,728.76
XS Rating Curve= 0
Exp/Cntr=.5,.3

Type RM Length L Ch R = 3 ,7063    ,,,
BEGIN DESCRIPTION:
422s9, "ACCESS ROAD"
N. Target Bridge.
This data comprised of elevation and distance estimates using hand level, pacing, and ocular estimation from digital photos, supported by TIN elevation and aerial photography.  Data obtained by FTN on Jan. 20, 2003.
END DESCRIPTION:
Bridge Culvert--1,0,-1,-1, 0
Deck Dist Width WeirC Skew NumUp NumDn MinLoCord MaxHiCord MaxSubmerge Is_Ogee
40,30,2.6,0, 8, 8, , , .95, 0, 0,0,,
       0  492.94  652.94  652.95  766.94  766.95  862.94    1084
      65    67.9    67.9    67.9    67.9    67.9    67.9      59
                            63.9    63.9
       0  492.94  652.94  652.95  766.94  766.95  862.94    1294
      65    67.9    67.9    67.9    67.9    67.9    67.9      58
                            63.9    63.9
Pier Skew, UpSta & Num, DnSta & Num=  ,712, 2 ,712, 2 , 0 , 0 , 0 ,,
     1.5     1.5
      40    63.9
     1.5     1.5
      40    63.9
BR Coef=-1 , 0 , 0 ,, 0 ,,,.8,-1,,1,
WSPro=,,,, 1 ,,,, 0 ,,,, 0 ,,,,-1 ,-1 ,-1 , 0 , 0 , 0 , 0 , 0
BC Design=,, 0 ,, 0 ,,,,,,

Type RM Length L Ch R = 1 ,7008.195,151.82,153.66,155.15
BEGIN DESCRIPTION:
 XS 2/4 for 422s09, Access Road, (North Target Center Bridge).  LIDAR Overbanks with interpolated and reconnaissance elevations between banks.  Interpolation performed between nearest surveyed sections (7702 and 6854).  LIDAR values used betweeen banks where banks wider than copied survey data.  Flow ineffective in low area beyond ROB, does not re-enter channel.
Bank Station offset =      4307
END DESCRIPTION:
XS GIS Cut Line= 4
      3149383.65    13936950.125     3150155.574    13936703.733
     3150222.981    13936677.807      3151223.72    13936369.289
#Sta/Elev= 30
       0   65.09  278.39   63.68  572.81   64.74  592.36   62.11  603.48   58.26
  610.45    56.7  618.43   56.89  656.11   54.94  686.84   48.16  688.38   48.81
  691.71   47.03  693.28   45.45  696.24   45.56  698.09   46.78  715.89   51.63
  777.46   53.26  815.47   53.82  878.39   52.33  944.95   57.24  990.74   58.88
 1097.02   57.69 1260.94   57.56 1410.95   58.24 1616.34   57.68 1637.32   59.13
 1753.67   62.03 1834.59   60.94 1913.24   63.91 1918.43   64.53 1929.73   64.35
#Mann= 4 ,-1 , 0
       0     .05       0  603.48    .035       0  777.46     .05       0
 1753.67     .99       0
#XS Ineff= 2 , 0
       0     620      65     800       0    64.4
Permanent Ineff=
       F       F
Bank Sta=656.11,715.89
XS Rating Curve= 0
Exp/Cntr=.5,.3

Type RM Length L Ch R = 1 ,6854.536,66.63,65.78,65.78
BEGIN DESCRIPTION:
422s1u.  Surveyed section.  XS 4/4.   XS 1/4 for 422s09, North Target Center Bridge.  LIDAR OB w/ interpolated and reconnaissance elevations between banks.  Interpolation performed between nearest surveyed sections (7702 and 6854). Blocked far LOB and extended ROB.   C/E increased 0.5/0.7.
Bank Station offset =      3688
END DESCRIPTION:
XS GIS Cut Line= 6
     3148860.373    13937334.722     3149505.731    13937098.918
     3150023.137    13936904.576     3150174.367    13936861.476
     3150862.983     13936609.93     3151275.341    13936470.759
#Sta/Elev= 30
       0   53.96  119.87   54.31  151.76   63.39   214.2   63.21  247.63   65.01
  949.42   64.14 1008.86   63.68 1062.43   61.33 1127.44   63.02 1202.21   62.11
 1237.31   56.89 1274.99   56.81 1307.26   48.81 1312.16   45.45 1338.26   53.13
 1423.76    54.9 1468.52    51.9  1523.3   57.22 1577.48   58.88 1667.03   57.69
 1895.47   57.32 1986.42   58.53 2039.81   57.48 2225.13   57.55 2256.79   59.28
  2338.7   59.89 2381.92   62.06 2505.51   62.03 2546.11   64.84 2565.37   62.96
#Mann= 4 ,-1 , 0
       0     .05       0 1237.31    .035       0 1423.76     .05       0
 1577.48     .99       0
#Block Obstruct= 1 ,-1
       0  154.86   63.44
Bank Sta=1274.99,1338.26
XS Rating Curve= 0
Exp/Cntr=.5,.3

Type RM Length L Ch R = 1 ,6788.754,105.9,105.9,108.76
BEGIN DESCRIPTION:
Copy of 422s1u.   XS 3/4.  Adjusted near ROB LIDAR elevations to LIDAR elevations at foot of u/s embankment, as for xs cut line overlays embankment partway up the slope.
Blocked far LOB at WS edge.   Adjusted elevations between CBs based on slope between nearest surveyed sections. C/E increased to 0.5/0.7 to prevent excessive negative WSEL.
Bank Station offset =      3686
END DESCRIPTION:
XS GIS Cut Line= 6
       3148883.8    13937396.413     3149529.158    13937160.609
     3150046.564    13936966.267     3150197.793    13936923.167
     3150765.048    13936723.329      3151285.65    13936548.076
#Sta/Elev= 30
       0   53.81  124.65   54.07  146.42   60.42  166.94   63.23   301.8   64.98
  638.43   64.72     709   58.56     894   52.61  976.48   54.86 1006.28   59.19
 1029.48   60.22 1059.88   59.78 1089.72   56.66 1276.44   56.66 1308.71   48.66
 1313.61    45.3 1339.71   52.98 1448.42    54.9 1477.71      53 1494.01    53.5
 1495.47    54.5 1496.14   57.62 1497.94   57.85 1583.55   59.21 1594.63   59.21
 2215.24   57.53  2329.9   59.54  2375.2   62.16 2507.37   62.32 2547.77   64.06
#Mann= 4 ,-1 , 0
       0     .05       0 1276.44    .035       0 1583.55     .05       0
 1594.63     .99       0
#XS Ineff= 2 , 0
       0 1276.44   58.86 1349.71       0   58.69
Permanent Ineff=
       F       F
#Block Obstruct= 4 ,-1
       0  176.64    63.6                          664.42    1028      60
  1080.5    1229    57.8
Bank Sta=1276.44,1339.71
XS Rating Curve= 0
Exp/Cntr=.5,.3

Type RM Length L Ch R = 2 ,6735.802,,,
BEGIN DESCRIPTION:
422s1  Townsen BLVD.
Culvert Length 86 ft obtained from recent aerial photo.
Set entrance loss = 0.3, a triple box culvert with headwall, beveled/chamfered inlet, and straight wingwalls on outer sides of outer boxes.
C/E increased to 0.5/0.7 in sections 2-4 to prevent excessive negative WSEL.
END DESCRIPTION:
Bridge Culvert--1,0,0,-1, 0
Deck Dist Width WeirC Skew NumUp NumDn MinLoCord MaxHiCord MaxSubmerge Is_Ogee
29.45,47,2.6,0, 9, 9, 58.69, , .95, 0, 0,0,,
       0 1196.96 1251.12 1296.96 1320.79 1327.06 1350.77 1396.96    3000
   58.86   58.86   58.86    58.9   58.82   58.79   58.69   58.69   58.69
       0       0       0       0       0       0       0       0       0
       0 1196.96 1251.12 1296.96 1320.79 1327.06 1350.77 1396.96    3000
   58.86   58.86   58.86    58.9   58.82   58.79   58.69   58.69   58.69
       0       0       0       0       0       0       0       0       0
BR Coef=-1 , 0 , 0 ,, 0 ,,,.8,0,,0,
WSPro=,,,, 1 ,,,, 0 ,,,, 0 ,,,,-1 ,-1 ,-1 , 0 , 0 , 0 , 0 , 0
Multiple Barrel Culv=2,6,10,86,.012,.5,1,12,2,46.7,46.6, 3,Culvert #1  , 0 ,10
 1302.96 1272.58 1313.68  1283.3 1324.91 1294.53
Culvert Bottom n=.012
BC Design=,, 0 ,, 0 ,,,,,,

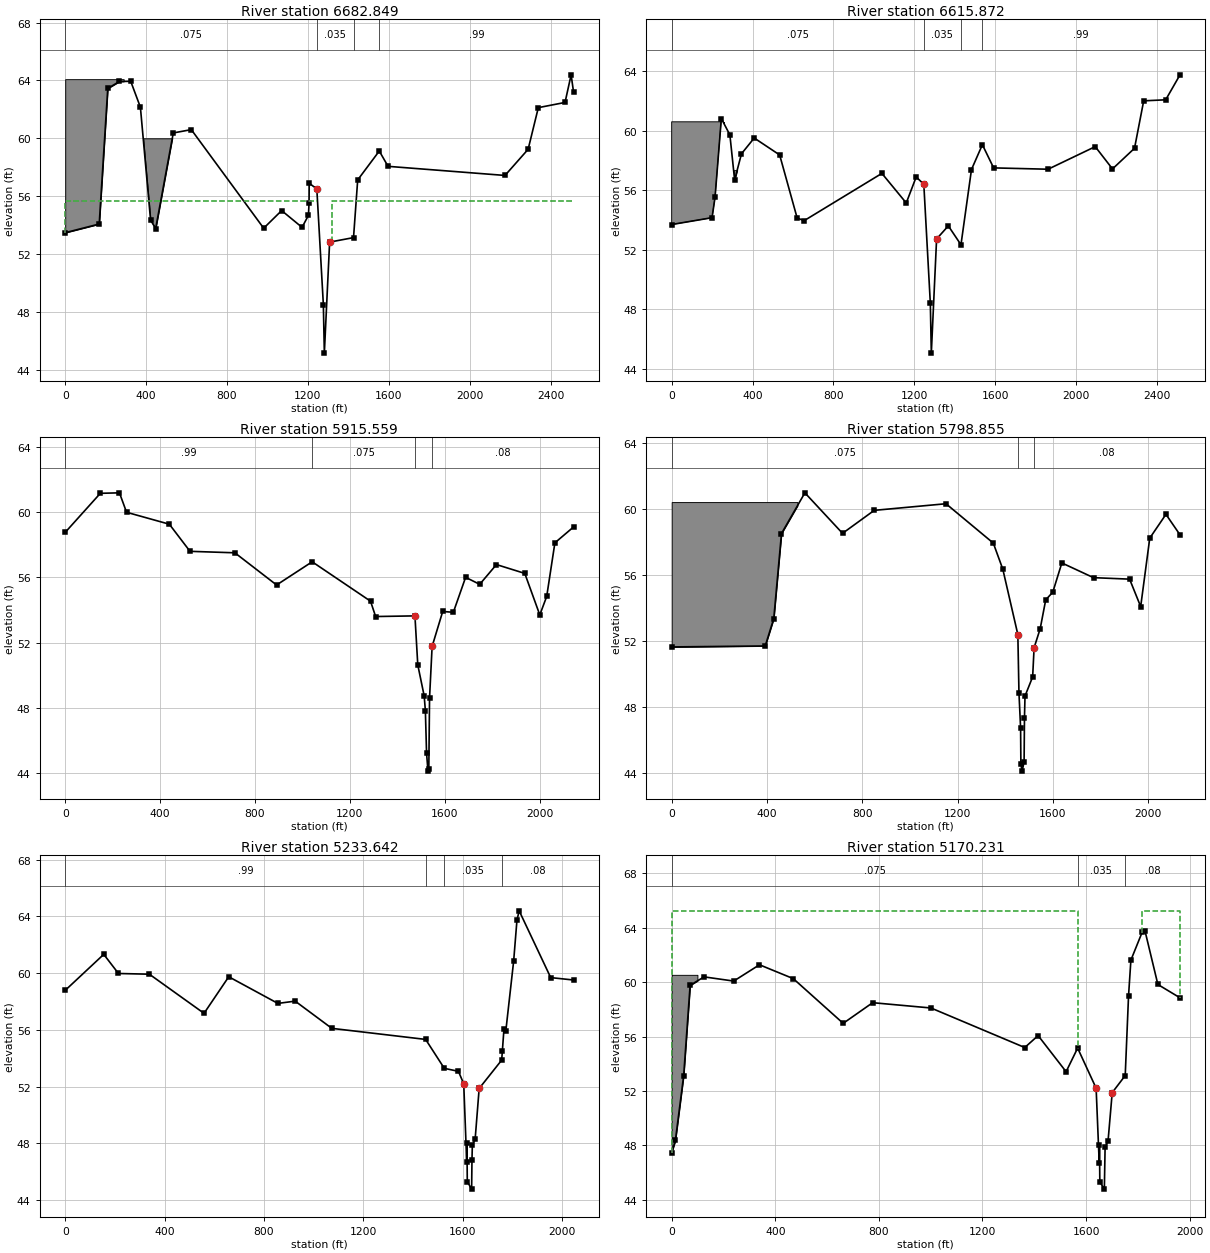
Type RM Length L Ch R = 1 ,6682.849,66.98,66.98,69.72
BEGIN DESCRIPTION:
Copy of 422s1u.   XS 2/4.   Adjusted elevations between CBs based on slope between nearest surveyed sections.
Blocked far LOB at WS edge.  C/E increased to 0.5/0.7 to prevent excessive negative WSEL.
Bank Station offset =      3719
END DESCRIPTION:
XS GIS Cut Line= 6
     3148952.199    13937486.987     3149597.557    13937251.183
     3150114.963     13937056.84     3150266.192    13937013.741
     3150868.138    13936800.646     3151321.731    13936651.166
#Sta/Elev= 30
       0   53.47  168.18   54.07   210.5   63.45   268.2   63.93  323.93   63.94
  371.73   62.15  422.06   54.34  447.23   53.76  534.35   60.37  623.38    60.6
  981.28   53.78  1070.1      55 1170.96   53.84 1202.55   54.67 1205.61   55.53
 1206.34   56.89 1244.02    56.5 1276.29    48.5 1281.19   45.14 1307.29   52.82
 1425.44   53.13 1446.06   57.12 1552.74   59.12 1596.13   58.06 2174.36   57.43
 2288.72   59.24 2339.08   62.12 2471.14   62.48 2501.23   64.39 2513.18   63.21
#Mann= 4 ,-1 , 0
       0    .075       0 1244.02    .035       0 1425.44     .05       0
 1552.74     .99       0
#XS Ineff= 2 , 0
       0 1244.02   55.65 1317.11       0   55.65
Permanent Ineff=
       F       F
#Block Obstruct= 2 ,-1
       0     289   64.09  377.61  533.15      60
Bank Sta=1244.02,1307.29
XS Rating Curve= 0
Exp/Cntr=.5,.3

Type RM Length L Ch R = 1 ,6615.872,701.44,700.31,700.31
BEGIN DESCRIPTION:
Copy of 422s1u.   XS 1/4.  Adjusted elevations between CBs based on slope between nearest surveyed sections.
Blocked far LOB not available for conveying flow
Bank Station offset =      3716
END DESCRIPTION:
XS GIS Cut Line= 6
     3148971.302    13937551.151     3149616.661    13937315.347
     3150134.067    13937121.005     3150285.296    13937077.905
     3150955.764    13936841.881     3151342.349    13936718.174
#Sta/Elev= 30
       0   53.69  199.68   54.15  214.51   55.53  245.63   60.82  287.84   59.72
  311.32   56.69  345.18   58.45  408.19   59.51  534.01   58.37  620.46   54.13
   655.1   53.95 1039.52   57.13 1160.05   55.14 1209.13   56.89 1246.81    56.4
 1279.08    48.4 1283.98   45.04 1310.08   52.72 1368.07    53.6 1430.58   52.33
 1482.58   57.39 1536.44   59.06 1592.11    57.5 1861.36   57.41 2094.53   58.93
 2179.88   57.43 2288.83   58.82 2334.16   62.01 2442.99   62.08 2513.73   63.76
#Mann= 4 ,-1 , 0
       0    .075       0 1246.81    .035       0 1430.58     .05       0
 1536.44     .99       0
#Block Obstruct= 2 ,-1
       0  256.63    60.6  256.63   344.5   57.35
Bank Sta=1246.81,1310.08
XS Rating Curve= 0
Exp/Cntr=.3,.1

Type RM Length L Ch R = 1 ,5915.559,170.21,116.7,44.27
BEGIN DESCRIPTION:
422v3
The ROB ditch is not blocked, as this area will effectively convey flow that re-enters main channel further d/s.
Bank Station offset =      3471
END DESCRIPTION:
XS GIS Cut Line= 6
     3149040.328    13938495.126     3149722.919    13938116.599
     3150288.524    13937805.832     3150437.108    13937761.983
     3150466.043    13937669.337     3150573.054     13937216.82
#Sta/Elev= 30
       0   58.75  148.06   61.14  228.65   61.17  258.61   59.98  438.94   59.25
   526.1   57.59  715.25    57.5  891.11   55.53 1041.09   56.95 1287.03   54.54
  1308.6    53.6 1474.28   53.64 1486.28   50.64 1513.28   48.74 1518.28   47.84
 1523.28   45.24 1529.28   44.14  1532.8   44.29 1535.87   48.62  1546.7   51.77
 1591.36   53.91 1636.19   53.86 1687.92      56  1747.3   55.57 1817.85   56.78
 1937.31   56.24  2000.6    53.7 2029.77   54.83 2064.26   58.11 2142.85   59.08
#Mann= 4 ,-1 , 0
       0     .99       0 1041.09    .075       0 1474.28    .035       0
  1546.7     .08       0
Bank Sta=1474.28,1546.7
XS Rating Curve= 0
Exp/Cntr=.3,.1

Type RM Length L Ch R = 1 ,5798.855,572.83,565.21,510.88
BEGIN DESCRIPTION:
422v4
The ROB ditch is not blocked, as this area will effectively convey flow that re-enters main channel further d/s.
LOB block at edge of section, drops off to adjacent WShed
Bank Station offset =      3530
END DESCRIPTION:
XS GIS Cut Line= 4
     3149871.848    13939202.538     3150454.702    13937917.213
     3150472.805    13937782.907     3150631.032    13937218.158
#Sta/Elev= 30
       0   51.64  392.58    51.7  428.51   53.36  460.88    58.5  559.03   60.96
   717.1   58.51  850.09    59.9 1151.22    60.3 1349.78   57.92 1389.74   56.34
 1452.79   52.39 1457.47   48.86 1464.37   46.74 1465.55   44.56 1470.49   44.13
 1479.04   44.69 1480.62   47.37 1482.86   48.67 1514.92   49.83 1521.01   51.59
 1546.67   52.75  1569.8   54.49 1599.37   54.95 1637.43   56.72 1770.32   55.83
 1921.86   55.74 1968.29   54.08 2006.42   58.22 2074.34   59.66 2133.32   58.42
#Mann= 3 ,-1 , 0
       0    .075       0 1452.79    .035       0 1521.01     .08       0
#Block Obstruct= 1 ,-1
       0     528    60.4
Bank Sta=1452.79,1521.01
XS Rating Curve= 0
Exp/Cntr=.3,.1

Type RM Length L Ch R = 1 ,5233.642,58.72,63.41,65.15
BEGIN DESCRIPTION:
422s2u.  Surveyed Section.  XS 4/4
Bank Station offset =      3363
0.99 in LOB for ineffective flow station related to structure
END DESCRIPTION:
XS GIS Cut Line= 4
      3151250.11    13939292.788     3151006.586    13937721.173
     3150945.455    13937604.743       3150940.3    13937280.012
#Sta/Elev= 30
       0   58.79   155.2   61.33  214.41   59.98  338.86   59.93  558.99   57.17
  658.45   59.75  856.29   57.87  925.91   58.03  1073.5   56.11 1451.18   55.33
  1526.3   53.29 1583.12   53.08 1604.57    52.2 1616.51    46.7  1617.4   48.05
 1618.88    45.3 1636.33   44.77 1637.76   46.84 1639.21   47.85 1650.59   48.31
 1666.68   51.87 1757.38   53.87 1760.11   54.52 1766.56   56.07 1773.82    55.9
 1805.57   60.86 1818.83   63.74 1827.78    64.4 1954.75   59.69 2046.64   59.52
#Mann= 4 ,-1 , 0
       0     .99       0 1451.18    .075       0  1526.3    .035       0
 1760.11     .08       0
Bank Sta=1604.57,1666.68
XS Rating Curve= 0
Exp/Cntr=.5,.3

Type RM Length L Ch R = 1 ,5170.231,158.22,158.22,161.97
BEGIN DESCRIPTION:
Copy of 422s2u.  XS 3/4.  Adjust elevations as needed.
Bank Station offset =      3329
LOB block at edge of section, drops off to adjacent WShed
END DESCRIPTION:
XS GIS Cut Line= 4
     3151507.288    13939263.114      3151054.74     13937681.58
     3150991.845    13937548.044     3150986.691    13937377.946
#Sta/Elev= 30
       0   47.46   14.33   48.35   46.31   53.12    71.3   59.77  125.14   60.39
  239.58   60.08  339.02   61.28  469.62   60.26  662.26   56.97  776.08   58.49
 1001.17    58.1 1363.43   55.19 1414.93   56.07 1523.01   53.41 1567.53   55.15
 1638.93    52.2 1650.87    46.7 1651.76   48.05 1653.24    45.3 1670.69   44.77
 1673.57   47.85 1684.95   48.31 1701.04   51.87 1751.27   53.13 1764.12      59
 1773.17   61.62 1816.56   63.67 1827.66   63.77 1877.37   59.83 1962.79   58.85
#Mann= 3 ,-1 , 0
       0    .075       0 1567.53    .035       0 1751.27     .08       0
#XS Ineff= 2 , 0
       0    1570   65.25    1815       0   65.25
Permanent Ineff=
       F       F
#Block Obstruct= 1 ,-1
       0   99.41   60.54
Bank Sta=1638.93,1701.04
XS Rating Curve= 0
Exp/Cntr=.5,.3

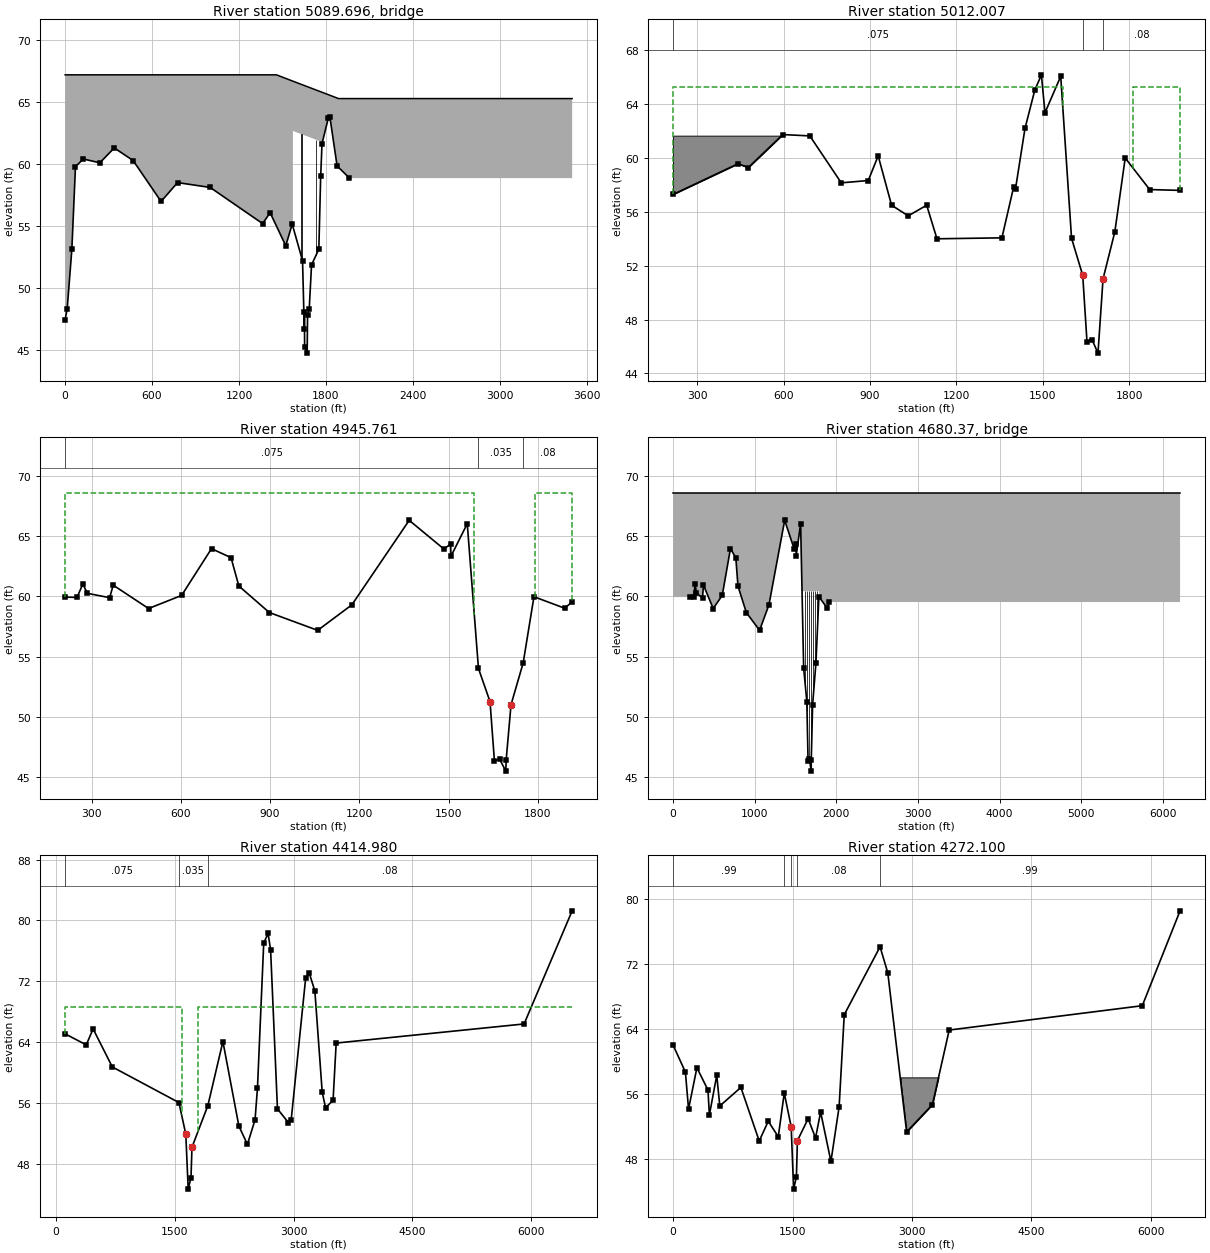
Type RM Length L Ch R = 3 ,5089.696,,,
BEGIN DESCRIPTION:
422s2 US Hwy 59 South Bound Ramp
END DESCRIPTION:
Bridge Culvert--1,0,-1,-1, 0
Deck Dist Width WeirC Skew NumUp NumDn MinLoCord MaxHiCord MaxSubmerge Is_Ogee
62.535,36,2.6,0, 8, 8, , , .95, 0, 3,3,,
       0  1458.6 1572.24 1572.24 1813.33 1813.33 1887.33    3500
   67.16   67.16   66.65   66.65   65.58   65.58   65.25   65.25
       0       0       0   62.65   61.58       0       0       0
       0  1458.6 1572.24 1572.24 1813.33 1813.33 1887.33    3500
   67.16   67.16   66.65   66.65   65.58   65.58   65.25   65.25
       0       0       0   62.65   61.58       0       0       0
Pier Skew, UpSta & Num, DnSta & Num=  ,1632.64, 4 ,1632.64, 4 , 3 , 3 , 0 ,,
       3       3     3.4     3.4
      40   58.33   58.33   62.65
       3       3     3.4     3.4
      40   58.33   58.33   62.65
Pier Skew, UpSta & Num, DnSta & Num=  ,1732.8, 4 ,1732.8, 4 , 3 , 3 , 0 ,,
       3       3     3.4     3.4
      40   57.91   57.91   62.65
       3       3     3.4     3.4
      40   57.91   57.91   62.65
BR Coef=-1 , 0 , 0 ,, 0 ,,,.8,-1,,0,
WSPro=,,,, 1 ,,,, 0 ,,,, 0 ,,,,-1 ,-1 ,-1 , 0 , 0 , 0 , 0 , 0
BC Design=,, 0 ,, 0 ,,,,,,

Type RM Length L Ch R = 1 ,5012.007,65.95,66.77,68.04
BEGIN DESCRIPTION:
Copy of 422s3u.  XS 4/4. Also is XS 2/4 for 422s2.   Adjust elevations as needed.
Bank Station offset =      3524
LOB block at edge of section, drops off to adjacent WShed
Performed bridge shift by adjusting cross-section station 215.49
END DESCRIPTION:
XS GIS Cut Line= 4
     3151656.095    13938994.665     3151254.755    13937763.113
     3151167.097    13937537.735     3151131.016    13937316.093
#Sta/Elev= 30
  215.49   57.28  441.56   59.56  476.75   59.27  596.75   61.72  690.74   61.62
  799.97   58.14  893.72   58.31   928.2   60.14  974.72   56.48  1032.6   55.69
 1096.74   56.48 1132.48   53.99 1358.14   54.06 1398.65   57.81 1405.37   57.69
 1438.27   62.17 1472.36   65.01 1495.34   66.15 1507.82   63.34 1562.48   66.04
 1600.11   54.03 1638.93   51.28 1653.78   46.35 1670.95   46.52 1691.97   45.51
 1709.54   51.02 1750.38   54.49 1786.58   59.98 1871.69   57.64 1977.17   57.58
#Mann= 3 , 0 , 0
  215.49    .075       0 1638.93    .035       0 1709.54     .08       0
#XS Ineff= 2 , 0
       0    1570   65.25    1815       0   65.25
Permanent Ineff=
       F       F
#Block Obstruct= 2 , 0
  215.49  600.24   61.64          215.49
Bank Sta=1638.93,1709.54
XS Rating Curve= 0
Exp/Cntr=.5,.3

Type RM Length L Ch R = 1 ,4945.761,517.53,530.25,534.58
BEGIN DESCRIPTION:
422s3u.  Surveyed section , XS 3/4.  Also is XS 1/4 for 422s2.
Bank Station offset =      3519
Performed bridge shift by adjusting cross-section station 211.32'
END DESCRIPTION:
XS GIS Cut Line= 4
      3151719.23    13938985.034      3151317.89    13937753.482
     3151223.796    13937491.345     3151208.333    13937362.483
#Sta/Elev= 30
  211.32   59.95  251.18   59.92  270.75   61.03  286.27   60.26  360.92    59.9
  372.75   60.94  491.73      59   602.7   60.09  703.13   63.97  768.74   63.22
  794.99   60.87  897.31   58.67 1059.89   57.19 1174.84   59.31 1367.38   66.32
 1484.39   63.93 1506.62   64.36 1507.82   63.34 1562.48   66.04 1600.11   54.03
 1638.93   51.28 1653.78   46.35 1670.95   46.52 1691.97   45.51 1693.31   46.46
 1709.54   51.02 1750.38   54.49 1786.58   59.98 1889.42   59.03 1914.92   59.54
#Mann= 3 ,-1 , 0
  211.32    .075       0 1600.11    .035       0 1750.38     .08       0
#XS Ineff= 2 , 0
  211.32 1586.32    68.6 1791.32  211.32    68.6
Permanent Ineff=
       F       F
Bank Sta=1638.93,1709.54
XS Rating Curve= 0
Exp/Cntr=.5,.3

Type RM Length L Ch R = 3 ,4680.37 ,,,
BEGIN DESCRIPTION:
US Hwy 59
Combination of 422s3, s4, s5, s6, and s7 (US 59 main lanes and on and off ramps)
Created bridge piers similiar to 422s4
Used the highest high cord and lowest low cord of the combined bridges.
The width of 432 feet was calculated as the distance from the upstream face of the 1st bridge to the downstream face of the last bridge.
END DESCRIPTION:
Bridge Culvert--1,0,-1,-1, 0
Deck Dist Width WeirC Skew NumUp NumDn MinLoCord MaxHiCord MaxSubmerge Is_Ogee
48.761,432,2.6,0, 6, 6, , , .95, 0, 0,0,,
       0 1591.82 1591.82 1789.82 1789.82 6211.32
    68.6    68.6    68.6    68.6    68.6    68.6
       0       0   60.44   60.44       0       0
       0 1591.82 1591.82 1789.82 1789.82 6211.32
    68.6    68.6    68.6    68.6    68.6    68.6
       0       0   60.44   60.44       0       0
Pier Skew, UpSta & Num, DnSta & Num=  ,1616.37, 4 ,1616.37, 4 , 3 , 3 , 0 ,,
    1.35    1.35     2.3     2.3
      45   58.14   58.14   60.44
    1.35    1.35     2.3     2.3
      45   58.14   58.14   60.44
Pier Skew, UpSta & Num, DnSta & Num=  ,1641.22, 4 ,1641.22, 4 , 3 , 3 , 0 ,,
    1.35    1.35     2.3     2.3
      45   58.14   58.14   60.44
    1.35    1.35     2.3     2.3
      45   58.14   58.14   60.44
Pier Skew, UpSta & Num, DnSta & Num=  ,1666.32, 4 ,1666.32, 4 , 3 , 3 , 0 ,,
    1.35    1.35     2.3     2.3
      45   58.14   58.14   60.44
    1.35    1.35     2.3     2.3
      45   58.14   58.14   60.44
Pier Skew, UpSta & Num, DnSta & Num=  ,1691.37, 4 ,1691.37, 4 , 3 , 3 , 0 ,,
    1.35    1.35     2.3     2.3
      45   58.14   58.14   60.44
    1.35    1.35     2.3     2.3
      45   58.14   58.14   60.44
Pier Skew, UpSta & Num, DnSta & Num=  ,1716.35, 4 ,1716.35, 4 , 3 , 3 , 0 ,,
    1.35    1.35     2.3     2.3
      45   58.14   58.14   60.44
    1.35    1.35     2.3     2.3
      45   58.14   58.14   60.44
Pier Skew, UpSta & Num, DnSta & Num=  ,1741.5, 4 ,1741.5, 4 , 3 , 3 , 0 ,,
    1.35    1.35     2.3     2.3
      45   58.14   58.14   60.44
    1.35    1.35     2.3     2.3
      45   58.14   58.14   60.44
Pier Skew, UpSta & Num, DnSta & Num=  ,1766.63, 4 ,1766.63, 4 , 3 , 3 , 0 ,,
    1.35    1.35     2.3     2.3
      45   58.14   58.14   60.44
    1.35    1.35     2.3     2.3
      45   58.14   58.14   60.44
BR Coef=-1 , 0 , 0 ,, 0 ,,,.8,-1,,0,
WSPro=,,,, 1 ,,,, 0 ,,,, 0 ,,,,-1 ,-1 ,-1 , 0 , 0 , 0 , 0 , 0
BC Design=,, 0 ,, 0 ,,,,,,

Type RM Length L Ch R = 1 ,4414.980,145.17,142.88,142.88
BEGIN DESCRIPTION:
422s7d.  Surveyed section.  XS 2/4.
Block is area separated by road construction of elevated highway, Townsen Blvd overpassing freeway.
Bank Station offset =      3446
Performed bridge shift by adjusting cross-section station 114.6'
END DESCRIPTION:
XS GIS Cut Line= 5
     3152230.353    13938963.738     3151789.618    13937595.756
      3151741.22    13937302.335     3151580.606    13936116.177
     3150435.481    13932837.252
#Sta/Elev= 30
   114.6    65.1  381.24   63.65  467.79   65.75  710.53   60.75 1551.74   56.07
 1638.93   51.91 1669.06   44.69 1704.32   46.19 1716.88    50.2    1917   55.65
 2107.58   64.09 2309.53   52.97 2417.27   50.57 2513.62   53.81 2544.33   57.99
  2623.2   77.04 2678.28   78.29 2710.09   76.15 2796.63   55.24 2935.37   53.43
 2970.39   53.82 3152.86   72.41 3197.19   73.14 3269.33   70.72 3362.05   57.42
 3404.37    55.4 3499.22   56.36 3538.39   63.89 5912.22    66.4 6519.33   81.27
#Mann= 3 ,-1 , 0
   114.6    .075       0 1551.74    .035       0    1917     .08       0
#XS Ineff= 2 , 0
       0 1586.32    68.6 1791.32       0    68.6
Permanent Ineff=
       F       F
#Block Obstruct= 2 , 0
   114.6                 2678.28   114.6   78.29
Bank Sta=1638.93,1716.88
XS Rating Curve= 0
Exp/Cntr=.5,.3

Type RM Length L Ch R = 1 ,4272.100,622.08,685.12,760.28
BEGIN DESCRIPTION:
Copy of 422s7d.  XS 1/4.  Adjusted elevations by -0.46 ft between CBs.
Placed block in ROB(not available for Trib flow)
The humps on rob appears to be from road construction; Townsen Blvd overpassing freeway.
Bank Station offset =      3486
END DESCRIPTION:
XS GIS Cut Line= 6
     3152296.997    13938958.739     3152175.275    13938578.358
     3151928.729    13937588.266     3151880.331    13937294.844
     3151771.091    13935822.051     3150632.919     13932860.48
#Sta/Elev= 30
       0   61.99  154.88   58.65  194.39   54.09   299.5   59.19  438.31   56.44
  455.93   53.37  548.68   58.25  586.83   54.48   851.7   56.76 1081.88   50.16
 1195.33    52.6 1321.24   50.68 1396.25   56.07 1483.44   51.91 1513.57   44.23
 1548.83   45.73 1561.39    50.2 1696.32   52.91 1789.14   50.53  1852.9   53.73
 1982.41   47.64 2085.41   54.39 2149.73   65.72 2599.33   74.09 2696.43   70.88
 2933.16   51.28 3257.15   54.65 3467.47   63.83  5892.3   66.83 6366.68   78.52
#Mann= 5 ,-1 , 0
       0     .99       0 1396.25    .075       0 1483.44    .035       0
 1561.39     .08       0 2599.33     .99       0
#Block Obstruct= 1 ,-1
    2859    3375      58
Bank Sta=1483.44,1561.39
XS Rating Curve= 0
Exp/Cntr=.3,.1