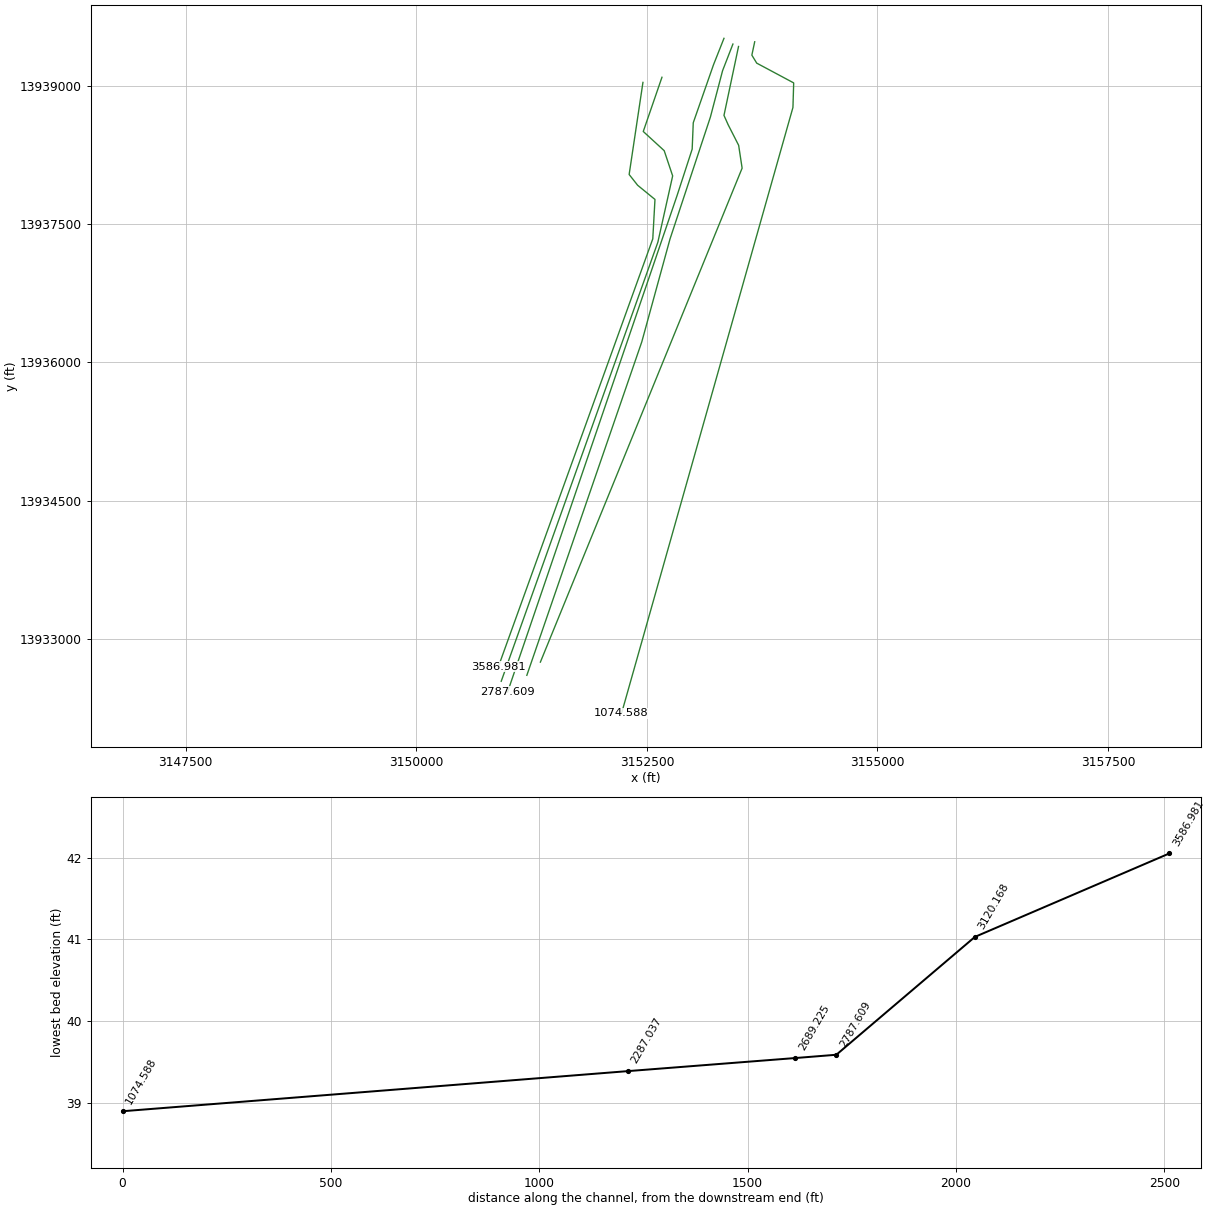
HEC-RAS study G103-48-00.prj: G103-48-00

--- G103-48-00.g07 (geometry) --- (continued)

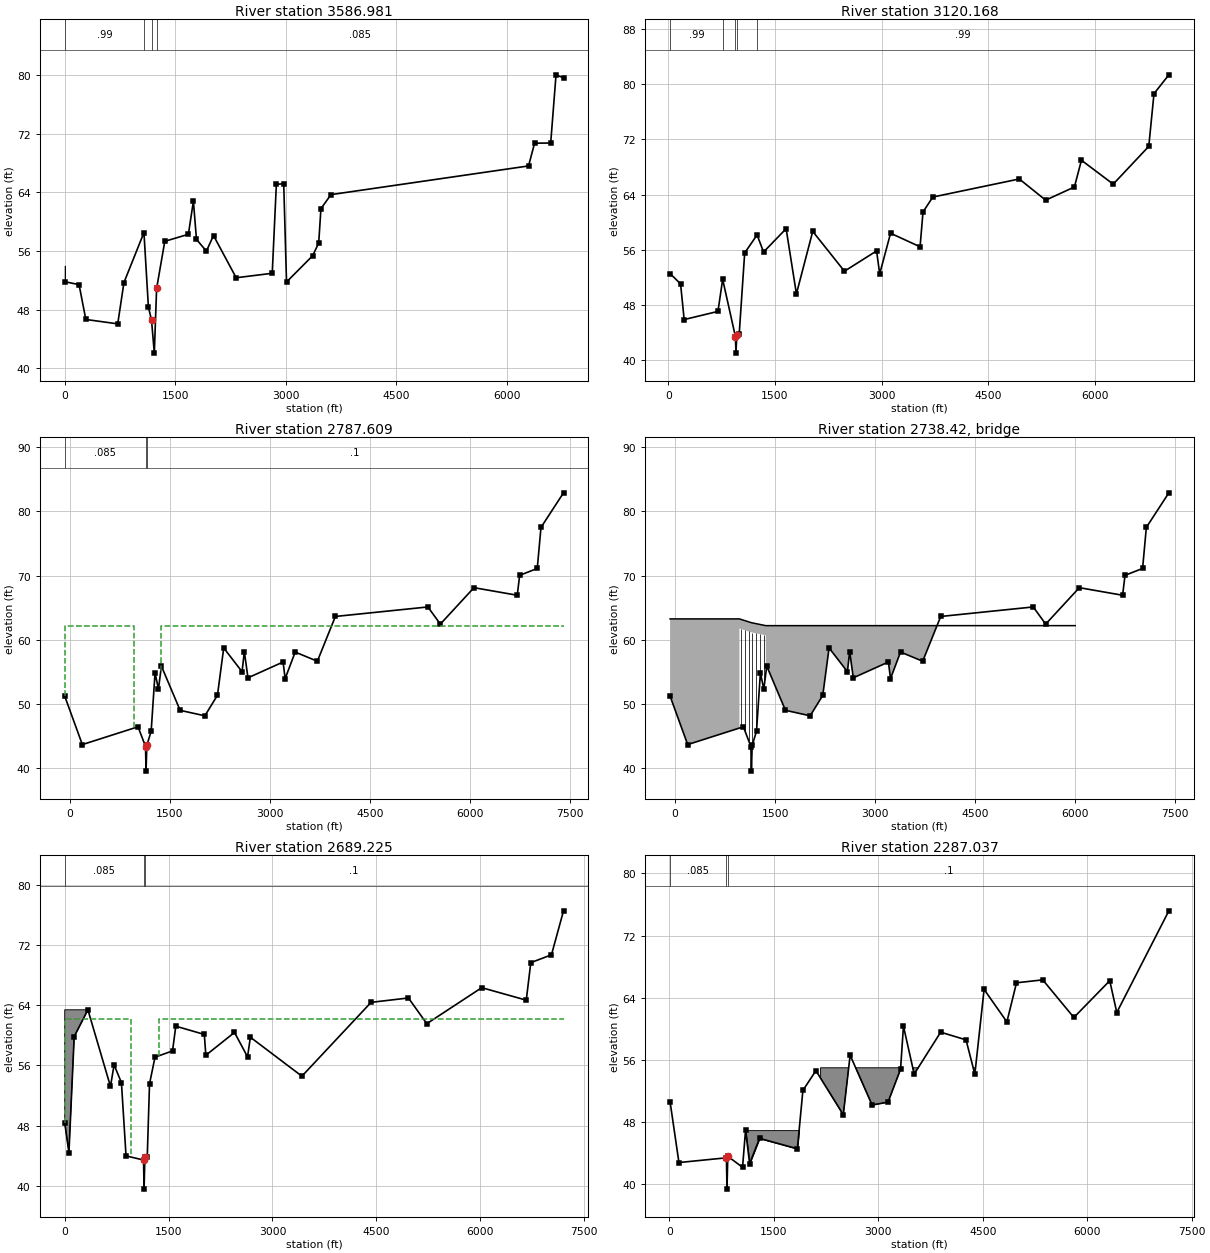
Type RM Length L Ch R = 1 ,3586.981,502.76,466.81,440.45
BEGIN DESCRIPTION:
422v5
Bank Station offset =      3784
Blocks in ROB low areas not available for main conveyance flow
END DESCRIPTION:
XS GIS Cut Line= 6
     3152456.881    13939035.699     3152307.282    13938037.263
     3152399.405    13937920.525     3152587.328    13937766.711
     3152563.595    13937339.523     3150888.427    13932697.884
#Sta/Elev= 30
       0   51.81  194.54   51.41  286.13   46.65  719.38   46.05  803.67   51.69
 1075.25   58.53 1135.64   48.37 1178.02   46.56 1215.98   42.05 1247.25   50.89
 1358.12   57.33 1678.55   58.29 1746.48   62.82 1788.18   57.59 1922.82   55.99
 2019.41   58.12 2327.08   52.35 2816.61   52.96 2872.51   65.12 2972.37    65.2
  3010.5   51.77 3365.32   55.36 3447.33   57.11  3477.5   61.79 3613.87   63.71
 6295.62   67.63 6377.42   70.74 6596.14   70.76  6668.6   80.08 6770.26   79.67
#Mann= 4 ,-1 , 0
       0     .99       0 1075.25    .078       0 1178.02    .036       0
 1247.25    .085       0
#Block Obstruct= 2 , 0
       0       2      54 1746.48       0   62.82
Bank Sta=1178.02,1247.25
XS Rating Curve= 0
Exp/Cntr=.3,.1

Type RM Length L Ch R = 1 ,3120.168,415.11,332.56,299.36
BEGIN DESCRIPTION:
Copy of 422s8u.  XS 4/4.  Adjusted elevations by +1.44 ft between CBs.
Blocks in ROB low areas not available for main conveyance flow
Bank Station offset =      4073
END DESCRIPTION:
XS GIS Cut Line= 6
 3152663.033889613939091.4603305     3152460.398     13938503.56
     3152687.383    13938295.507     3152779.095    13938021.917
     3152618.579    13937302.957 3150920.2190634 13932542.236868
#Sta/Elev= 30
    25.6   52.55  173.17   51.06  223.58   45.89  698.86   47.07  765.39   51.71
  944.68   43.42  952.32   41.03  964.09   43.61  998.21   43.84 1074.99   55.54
 1249.53   58.15  1340.5   55.67 1657.89   59.05 1802.63   49.61 2032.15   58.66
 2478.22   52.89 2930.33   55.83 2974.16   52.51 3126.96   58.39 3541.97   56.43
 3583.29   61.47 3721.23   63.63  4937.3   66.25 5308.51   63.18 5712.89   65.09
 5811.67   68.96 6258.87    65.5 6758.87   70.97  6832.2    78.6 7041.51   81.33
#Mann= 5 ,-1 , 0
    25.6     .99       0  765.39    .085       0  944.68     .04       0
  964.09      .1       0 1249.53     .99       0
#Block Obstruct= 2 , 0
    25.6                 1647.95    25.6   59.07
Bank Sta=944.68,964.09
XS Rating Curve= 0
Exp/Cntr=.5,.3

Type RM Length L Ch R = 1 ,2787.609,172.64,98.38,91.48
BEGIN DESCRIPTION:
422s8u.  Surveyed section.  XS 3/4
Bank Station offset =      3781
Performed bridge shift by adjusting cross-section station -73.28'
END DESCRIPTION:
XS GIS Cut Line= 6
     3153335.426    13939513.595     3153221.783    13939226.553
     3153002.497    13938598.329     3152990.644    13938311.875
     3152826.674     13937808.11     3150989.494     13932426.25
#Sta/Elev= 30
  -73.28   51.26  190.66   43.72 1025.54   46.49  1138.1   43.42 1145.74   39.59
 1157.51   43.61 1222.43   45.79 1280.81   54.88 1331.82   52.35 1375.85   55.94
 1656.68   49.05 2027.47    48.2 2216.08   51.39 2310.29   58.76  2585.3   55.06
 2619.11    58.2 2673.61   54.11 3200.18   56.57 3231.03   53.98 3381.59   58.12
  3713.8   56.69  3984.2   63.66 5371.15   65.14 5557.65   62.47 6061.86   68.14
 6710.92   66.96 6746.69   70.06 7010.57   71.13 7066.64   77.52 7404.35    82.9
#Mann= 3 , 0 , 0
  -73.28    .085       0  1138.1     .04       0 1157.51      .1       0
#XS Ineff= 2 , 0
  -73.28  961.72   62.23 1366.72  -73.28   62.23
Permanent Ineff=
       F       F
Bank Sta=1138.1,1157.51
XS Rating Curve= 0
Exp/Cntr=.5,.3

Type RM Length L Ch R = 3 ,2738.42 ,,,
BEGIN DESCRIPTION:
422s8  SOUTHERN PACIFIC RR, Railroad Bridge
END DESCRIPTION:
Bridge Culvert--1,0,-1,-1, 0
Deck Dist Width WeirC Skew NumUp NumDn MinLoCord MaxHiCord MaxSubmerge Is_Ogee
44.89,8.6,2.6,0, 8, 7, , , .95, 0, 0,0,,
  -73.28       0  966.68  966.68 1145.73 1361.92 1361.92    6000
   63.28   63.28   63.28   63.28   62.69   62.23   62.23   62.23
       0       0       0   61.78   61.19   60.73       0       0
       0  966.68  966.68 1145.73 1361.92 1361.92    6000
   63.28   63.28   63.28   62.69   62.23   62.23   62.23
       0       0   61.78   61.19   60.73       0       0
Pier Skew, UpSta & Num, DnSta & Num=  ,991.68, 2 ,991.68, 2 , 0 , 0 , 0 ,,
     1.5     1.5
   39.59   61.78
     1.5     1.5
   39.59   61.78
Pier Skew, UpSta & Num, DnSta & Num=  ,1048.11, 2 ,1048.11, 2 , 0 , 0 , 0 ,,
     1.5     1.5
   39.59   61.78
     1.5     1.5
   39.59   61.78
Pier Skew, UpSta & Num, DnSta & Num=  ,1104.54, 2 ,1104.54, 2 , 0 , 0 , 0 ,,
     1.5     1.5
   39.59   61.78
     1.5     1.5
   39.59   61.78
Pier Skew, UpSta & Num, DnSta & Num=  ,1160.97, 2 ,1160.97, 2 , 0 , 0 , 0 ,,
     1.5     1.5
   39.59   61.78
     1.5     1.5
   39.59   61.78
Pier Skew, UpSta & Num, DnSta & Num=  ,1217.4, 2 ,1217.4, 2 , 0 , 0 , 0 ,,
     1.5     1.5
   39.59   61.78
     1.5     1.5
   39.59   61.78
Pier Skew, UpSta & Num, DnSta & Num=  ,1273.83, 2 ,1273.83, 2 , 0 , 0 , 0 ,,
     1.5     1.5
   39.59   61.78
     1.5     1.5
   39.59   61.78
Pier Skew, UpSta & Num, DnSta & Num=  ,1330.26, 2 ,1330.26, 2 , 0 , 0 , 0 ,,
     1.5     1.5
   39.59   61.78
     1.5     1.5
   39.59   61.78
BR Coef=-1 , 0 , 0 ,, 0 ,,,.8,-1,,0,
WSPro=,,,, 1 ,,,, 0 ,,,, 0 ,,,,-1 ,-1 ,-1 , 0 , 0 , 0 , 0 , 0
BC Design=,, 0 ,, 0 ,,7,1064.97,991.68,56.43,1.5

Type RM Length L Ch R = 1 ,2689.225,223.62,402.19,398.76
BEGIN DESCRIPTION:
Copy of 422s8u.  XS 2/4.  Adjusted elevations by -0.04 ft between CBs.
Far left overbank blocked at watershed divide
Bank Station offset =      3854
END DESCRIPTION:
XS GIS Cut Line= 6
     3153432.422    13939451.418      3153320.56    13939163.336
     3153188.199    13938659.571     3152750.132    13937337.116
     3152444.603    13936223.225     3151198.047    13932606.996
#Sta/Elev= 30
       0   48.35   60.78   44.42  136.64   59.83  334.73    63.4  660.42   53.21
  712.77   56.07   818.7   53.71  885.31   43.97  1138.1   43.42 1145.74   39.55
 1157.51   43.81 1191.63   43.84 1224.55   53.55 1303.51    57.1 1556.81   57.93
 1603.84   61.22 2015.84   60.12 2037.68   57.35 2451.56   60.39 2640.21   57.14
 2680.86   59.75 3425.05   54.57 4424.25   64.39  4963.4   64.97 5228.88   61.55
 6022.04   66.34 6665.01   64.68 6730.63   69.67 7029.23   70.71 7203.15   76.56
#Mann= 3 , 0 , 0
       0    .085       0  1138.1     .04       0 1157.51      .1       0
#XS Ineff= 2 , 0
       0     961   62.23    1366       0   62.23
Permanent Ineff=
       F       F
#Block Obstruct= 1 ,-1
       0     335    63.4
Bank Sta=1138.1,1157.51
XS Rating Curve= 0
Exp/Cntr=.5,.3

Type RM Length L Ch R = 1 ,2287.037,751.84,1212.45,1149.4
BEGIN DESCRIPTION:
Copy of 422s8u.  XS 1/4.  Adjusted elevations by -0.2 ft between CBs.
Bank Station offset =      4183
The cross section crosses a pond on the ROB. Hence Blocked.
END DESCRIPTION:
XS GIS Cut Line= 6
 3153493.278233613939425.1663262     3153335.586    13938678.214
     3153379.782    13938578.773     3153494.691    13938353.375
     3153532.257    13938105.878 3151344.771130113932749.9313821
#Sta/Elev= 30
    11.7   50.63  138.74   42.81  820.89   43.42  828.53   39.39   840.3   43.61
 1052.27    42.2 1095.23   46.98  1153.6   42.68 1296.31   45.92 1839.03   44.58
 1918.62   52.09 2105.66   54.63 2498.41   48.96  2596.7   56.62 2912.22   50.21
 3141.09   50.58 3320.76   54.82 3362.09   60.36 3516.17   54.19 3896.74   59.58
 4260.59   58.59 4387.12   54.17 4520.06   65.08 4847.23    60.9  4985.1   65.93
 5362.08   66.31 5808.72   61.47 6324.08    66.2 6425.09   62.11  7172.7   75.19
#Mann= 3 ,-1 , 0
    11.7    .085       0  820.89     .04       0   840.3      .1       0
#Block Obstruct= 2 ,-1
 1095.23  1876.7   46.98  2172.7  4436.7      55
Bank Sta=820.89,840.3
XS Rating Curve= 0
Exp/Cntr=.3,.1

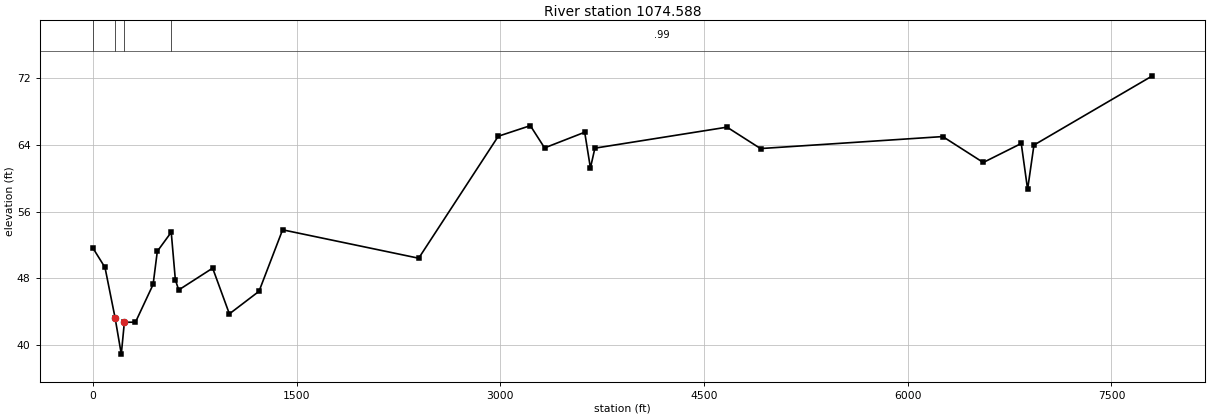
Type RM Length L Ch R = 1 ,1074.588,525.57,505.9,443.75
BEGIN DESCRIPTION:
422v6
Bank Station offset =      4790
The cross section crosses a pond on the ROB. Hence Blocked.
END DESCRIPTION:
XS GIS Cut Line= 6
     3153668.694    13939476.289     3153637.819    13939331.405
     3153690.616    13939244.636     3154091.392     13939030.39
     3154083.327    13938764.188     3152224.822    13932194.138
#Sta/Elev= 30
       0   51.66   90.03    49.3  163.84   43.29  209.99    38.9  232.72   42.73
  314.27   42.73   444.2   47.26  475.19   51.24  577.65   53.53  607.99   47.82
  632.63    46.6  882.61   49.22 1005.73   43.73 1223.97   46.44 1397.65   53.82
 2399.51   50.41 2985.48   65.05 3221.53   66.32 3326.42   63.65 3621.81   65.53
 3663.91   61.24 3696.88   63.62 4669.69   66.14 4916.47   63.57 6257.94   65.01
 6556.15    61.9 6835.87   64.18 6882.63   58.67  6929.4   63.99 7801.68    72.3
#Mann= 4 ,-1 , 0
       0     .09       0  163.84    .055       0  232.72    .095       0
  577.65     .99       0
#Block Obstruct= 2 , 0
       0                     600       0   49.22
Bank Sta=163.84,232.72
XS Rating Curve= 0
Exp/Cntr=.3,.1