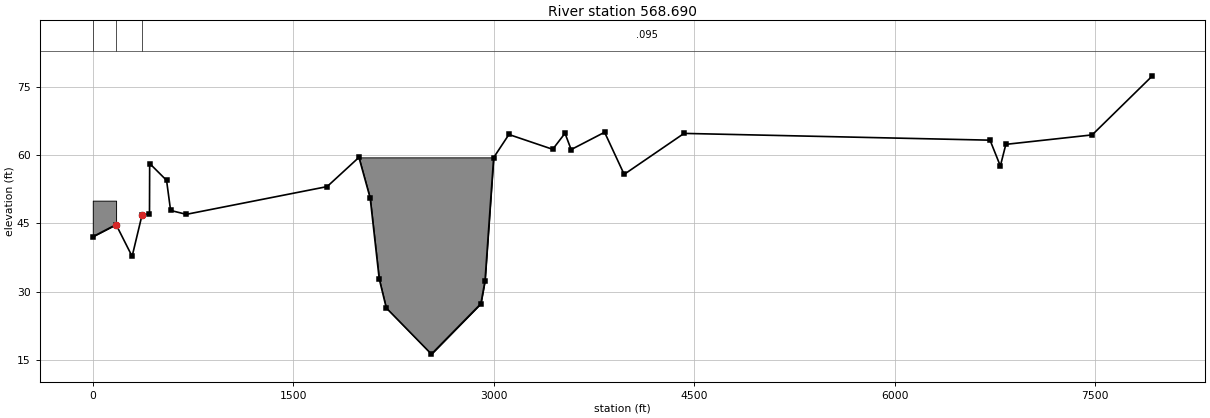
HEC-RAS study G103-48-00.prj: G103-48-00

--- G103-48-00.g07 (geometry) --- (continued)

Type RM Length L Ch R = 1 ,568.690 ,501.97,568.69,645.81
BEGIN DESCRIPTION:
422v7 Blocked LOB, LOB at watershed divide
ROB block is area not available for flow.
Bank Station offset =      4706
END DESCRIPTION:
XS GIS Cut Line= 4
     3153978.225    13939617.676     3154237.295    13939279.863
     3154243.923    13938686.927     3152787.824    13931931.404
#Sta/Elev= 30
       0   42.07  174.45   44.73  294.45   37.75  369.45   46.95  424.45      47
  425.72   58.17   552.1   54.47  582.32   47.85  699.72   46.99 1753.63   53.09
 1991.68   59.52 2075.86   50.56  2143.4   32.81 2196.39    26.4 2533.93   16.25
 2904.03   27.34 2935.16   32.39 2999.85   59.47  3113.9   64.55 3441.52   61.29
 3533.59   64.82 3579.62   61.23 3829.92   65.04 3976.31   55.78 4424.29   64.79
 6714.18    63.3 6791.37   57.62 6832.49   62.38 7478.44   64.46 7929.36   77.45
#Mann= 3 , 0 , 0
       0     .09       0  174.45    .055       0  369.45    .095       0
#Block Obstruct= 2 ,-1
    1992    3016   59.52       0  174.45      50
Bank Sta=174.45,369.45
XS Rating Curve= 0
Exp/Cntr=.3,.1

Chan Stop Cuts=-1